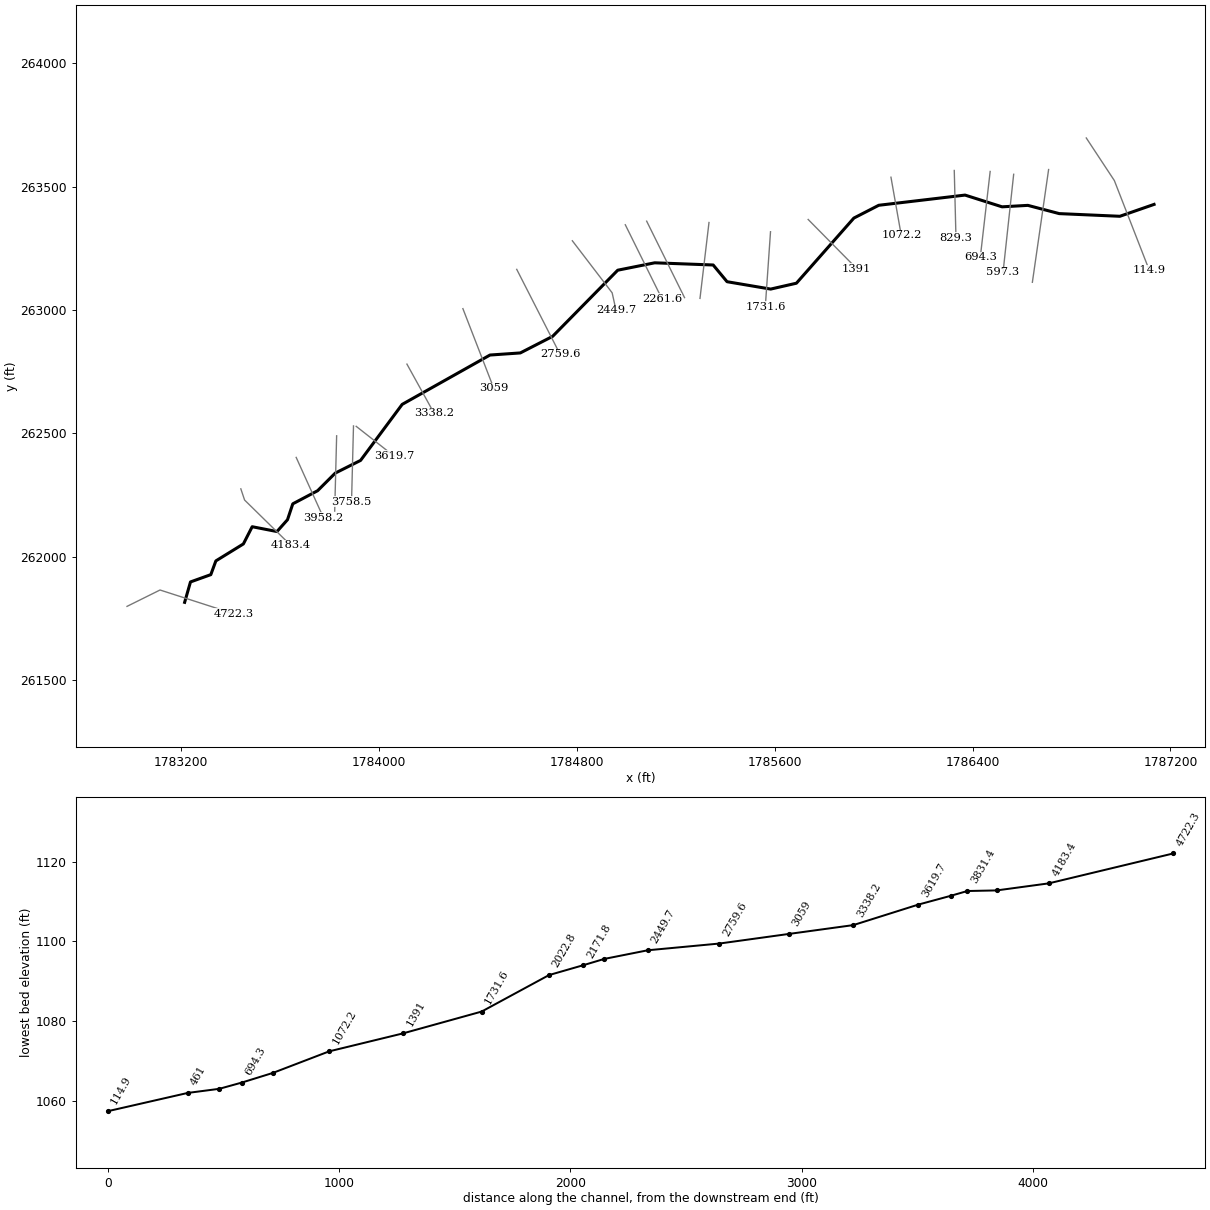
--- WBSIMPCK.prj (project) ---

Proj Title=WBSIMPCK
Current Plan=p01
Default Exp/Contr=0,0
English Units
Geom File=g01
Flow File=f01
Plan File=p01
BEGIN DESCRIPTION:
END DESCRIPTION:
DSS Export Rating Curves= 0
DSS Export Rating Curve Sorted= 0
DSS Export Volume Flow Curves= 0
DXF OffsetX= 0
DXF OffsetY= 0
DXF ScaleX= 0
DXF ScaleY= 0

--- WBSIMPCK.p01 (plan) ---

Plan Title=Floodplain
Program Version=4.00
Geom File=g01
Flow File=f01
K Sum by GR=0
Std Step Tol=0.01
Critical Tol=0.01
Num of Std Step Trials=20
Max Error Tol=0.3
Flow Tol Ratio=0.001
Split Flow NTrial=30
Split Flow Tol=0.02
Split Flow Ratio=0.02
Log Output Level=0
Friction Slope Method=1
Unsteady Friction Slope Method=2
Unsteady Bridges Friction Slope Method=1
Global Log Level=0
CheckData=False
Run HTab=0
Run UNet=0
Run PostProcess=0
UNET Theta=0
UNET Theta Warmup=0
UNET ZTol=0
UNET ZSATol=0
UNET MxIter=0
UNET MaxInSteps=0
UNET DtIC=0
UNET DtMin=0
UNET MaxCRTS=0
UNET WFStab=0
UNET SFStab=0
UNET WFX=0
UNET SFX=0
UNET DSS MLevel=0
UNET DZMax Abort=0
UNET Convert EG Bridges=0
UNET Use Existing IB Tables=0
UNET Froude Limit=0
UNET Froude Power=0
Write IC File=0
Echo Input=False
Echo Output=False
Write Detailed=0

--- WBSIMPCK.f01 (steady flow) ---

Flow Title=NFF Regression Equation
Program Version=4.10
Number of Profiles= 1
Profile Names=P100yr
River Rch & RM=WBSIMPCK,Main            ,4722.3
1115.017
River Rch & RM=WBSIMPCK,Main            ,114.9
 1386.33
River Rch & RM=WBSIMPCK,Main            ,114.9
1193.611
Boundary for River Rch & Prof#=WBSIMPCK,Main            , 1
Up Type= 0
Dn Type= 1
Dn Known WS=1061.42
DSS Import GetInterval= 0
DSS Import GetPeak= 0
DSS Import FillOption= 0

--- WBSIMPCK.g01 (geometry) ---

Geom Title=USGS 10m DEM
Program Version=4.10

River Reach=WBSIMPCK        ,Main
Reach XY= 30
     1783213.571      261814.891     1783237.203      261897.541
     1783319.413      261927.109     1783339.821      261982.782
     1783451.106      262051.538     1783486.763        262121.3
     1783586.998      262101.769      1783629.59      262149.796
     1783650.947      262214.066     1783751.341      262267.234
     1783822.694      262338.646     1783925.076      262390.035
     1784093.371      262617.126     1784448.412       262817.06
     1784571.037      262825.566     1784701.719      262892.758
     1784965.028      263160.842     1785114.576      263190.808
     1785351.072      263181.966      1785407.16      263114.222
     1785583.545      263084.332     1785687.665      263108.139
     1785920.049       263372.13     1786020.694      263423.952
     1786369.623      263465.268     1786519.331      263417.683
     1786623.657        263423.6     1786750.532      263390.174
     1786995.639      263379.359     1787134.038      263427.524

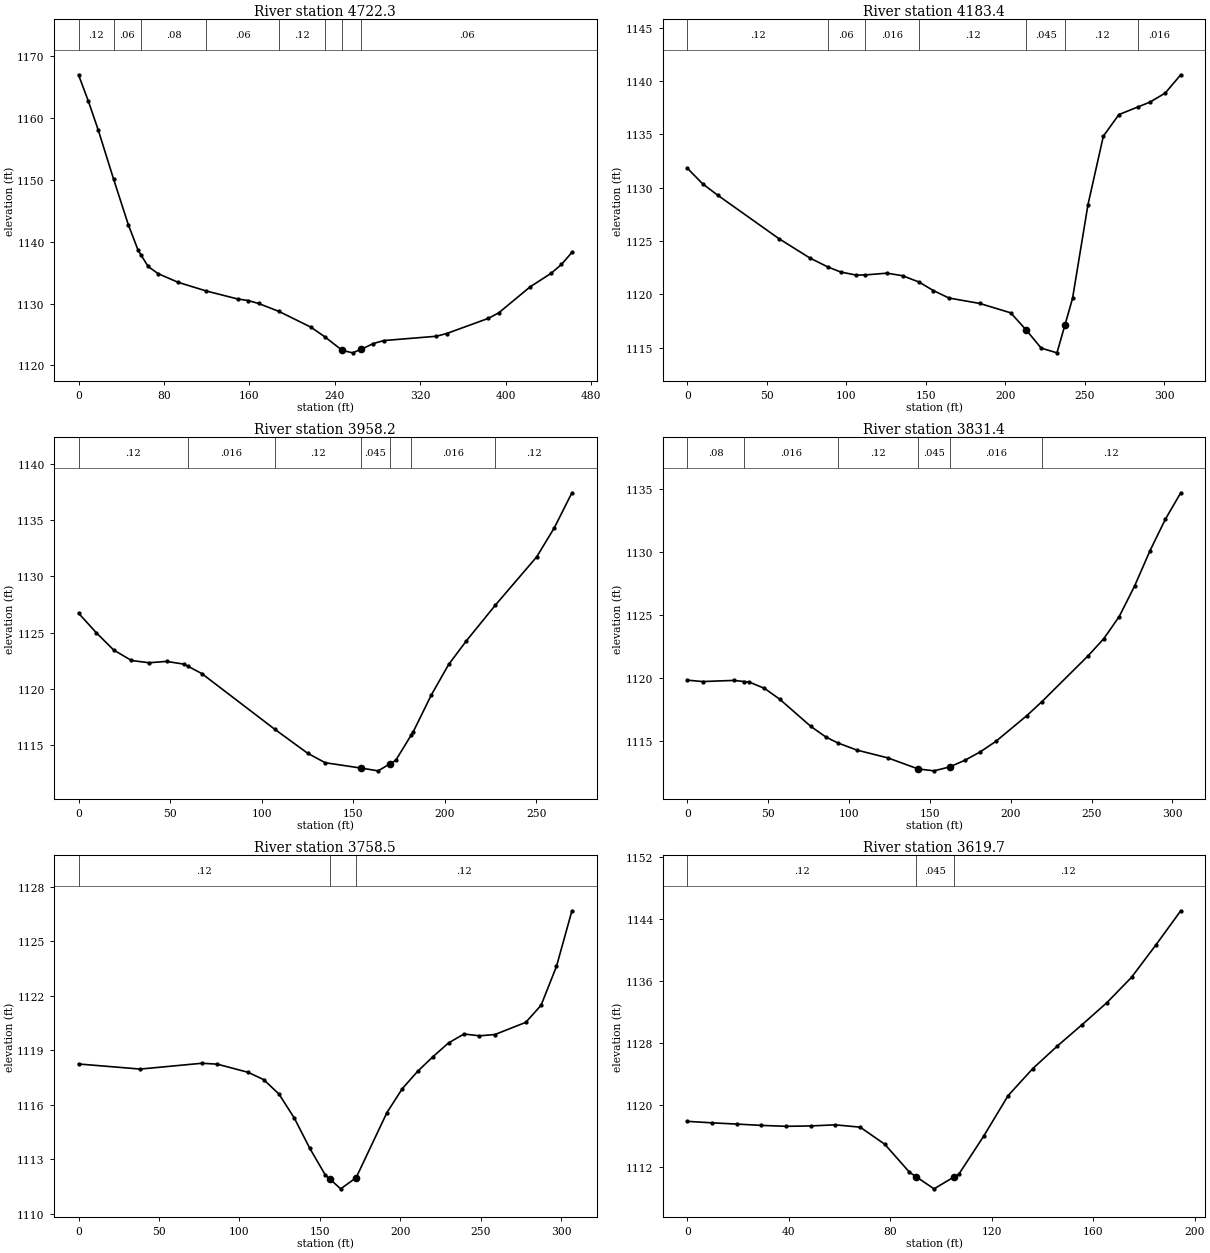
Type RM Length L Ch R = 1 ,4722.3  ,540.2,538.9,513.8
XS GIS Cut Line= 3
     1782980.549      261798.525     1783114.021      261864.857
     1783411.915       261768.63
#Sta/Elev= 30
       0 1167.04     9.3 1162.72    18.6 1158.03   32.891150.123    46.6 1142.79
    55.9  1138.6   58.371137.912    65.2 1136.01    74.5 1134.85    93.2 1133.45
  119.421132.053     149 1130.75   158.8  1130.5   168.6 1130.02  187.531128.747
   217.5  1126.2   230.41124.659   246.9 1122.44   256.7 1122.03   264.4 1122.58
   276.2 1123.54     286 1124.02   334.9 1124.71   344.7 1125.15   383.8 1127.61
   393.6 1128.51     423 1132.72   442.5 1134.89   452.3 1136.34   462.1 1138.29
#Mann= 8 ,-1 , 0
       0     .12       0   32.89     .06       0   58.37     .08       0
  119.42     .06       0  187.53     .12       0   230.4    .016       0
   246.9    .045       0   264.4     .06       0
Bank Sta=246.9,264.4
XS Rating Curve= 0 ,0
Exp/Cntr=0.3,0.1

Type RM Length L Ch R = 1 ,4183.4  ,254.7,225.2,210.9
XS GIS Cut Line= 3
     1783440.828      262274.799     1783456.035       262229.44
     1783643.309      262045.322
#Sta/Elev= 28
       0 1131.83     9.6 1130.37    19.1  1129.3    57.6 1125.23      77 1123.42
   88.221122.587    96.5  1122.1   106.2 1121.81  111.851121.822   125.6 1121.99
   135.4 1121.75  145.791121.159   154.8 1120.36   164.6 1119.66     184 1119.15
   203.5 1118.27   213.2 1116.67   222.7 1114.96   232.6 1114.52   237.7 1117.17
   242.4 1119.62   252.1  1128.4   261.8 1134.84   271.6 1136.86  283.511137.572
     291 1138.02   300.7 1138.87   310.5 1140.59
#Mann= 7 ,-1 , 0
       0     .12       0   88.22     .06       0  111.85    .016       0
  145.79     .12       0   213.2    .045       0   237.7     .12       0
  283.51    .016       0
Bank Sta=213.2,237.7
XS Rating Curve= 0 ,0
Exp/Cntr=0.3,0.1

Type RM Length L Ch R = 1 ,3958.2  ,145.2,126.7,101.2
XS GIS Cut Line= 2
     1783664.681      262402.185     1783775.486      262156.567
#Sta/Elev= 25
       0 1126.74     9.6 1125.02    19.2 1123.47    28.9 1122.54    38.5 1122.34
    48.1 1122.46    57.7 1122.21   59.711122.036    67.4 1121.37  107.081116.446
   125.1 1114.31   134.7 1113.47     154    1113   163.6 1112.75     170 1113.37
   173.2 1113.68  181.751115.951   182.8 1116.23   192.5 1119.44   202.1 1122.19
   211.7 1124.27  227.581127.449   250.2 1131.74   259.8 1134.32   269.4 1137.42
#Mann= 7 ,-1 , 0
       0     .12       0   59.71    .016       0  107.08     .12       0
     154    .045       0     170     .12       0  181.75    .016       0
  227.58     .12       0
Bank Sta=154,170
XS Rating Curve= 0 ,0
Exp/Cntr=0.3,0.1

Type RM Length L Ch R = 1 ,3831.4  ,75.2,72.9,80.7
XS GIS Cut Line= 2
     1783828.289      262489.793     1783820.414      262184.648
#Sta/Elev= 27
       0 1119.81     9.5  1119.7    28.6 1119.79   35.191119.701    38.2 1119.66
    47.7 1119.16    57.2 1118.29    76.3 1116.14    85.8 1115.28   93.081114.818
   104.9 1114.25     124 1113.63   142.8 1112.75   152.6  1112.6   162.2 1112.91
   171.7 1113.44   181.2 1114.11   190.8 1114.94   209.9 1116.98  219.291118.097
     248 1121.76   257.6 1123.11   267.1 1124.86   276.6 1127.28   286.2 1130.11
   295.7 1132.61   305.2 1134.71
#Mann= 6 ,-1 , 0
       0     .08       0   35.19    .016       0   93.08     .12       0
   142.8    .045       0   162.2    .016       0  219.29     .12       0
Bank Sta=142.8,162.2
XS Rating Curve= 0 ,0
Exp/Cntr=0.3,0.1

Type RM Length L Ch R = 1 ,3758.5  ,99.6,138.8,174.4
XS GIS Cut Line= 2
     1783896.447      262529.802     1783888.532      262223.076
#Sta/Elev= 25
       0 1118.25    38.4 1117.97    76.7 1118.29    86.3 1118.24   105.5 1117.79
   115.1 1117.39   124.6  1116.6   134.2 1115.27   143.8 1113.61   153.4 1112.15
   156.5  1111.9     163 1111.38   172.6 1111.99   191.8 1115.58   201.4  1116.9
   210.9 1117.85   220.5 1118.66   230.1 1119.41   239.7  1119.9   249.3  1119.8
   258.9 1119.87   278.1 1120.54   287.6 1121.48   297.2 1123.62   306.8 1126.68
#Mann= 3 ,-1 , 0
       0     .12       0   156.5    .045       0   172.6     .12       0
Bank Sta=156.5,172.6
XS Rating Curve= 0 ,0
Exp/Cntr=0.3,0.1

Type RM Length L Ch R = 1 ,3619.7  ,296.7,281.5,266.6
XS GIS Cut Line= 2
     1783907.424      262528.051     1784060.233      262407.808
#Sta/Elev= 23
       0 1117.91     9.7 1117.72    19.4 1117.56    29.2 1117.39    38.9 1117.27
    48.6 1117.32    58.3 1117.46    68.1 1117.16    77.8 1114.95    87.5 1111.35
    90.2 1110.75    97.2  1109.2   105.2 1110.76     107 1111.11   116.7 1115.97
   126.4 1121.24   136.1 1124.72   145.8 1127.64   155.6 1130.41   165.3 1133.23
     175  1136.5   184.7 1140.72   194.4 1145.09
#Mann= 3 ,-1 , 0
       0     .12       0    90.2    .045       0   105.2     .12       0
Bank Sta=90.2,105.2
XS Rating Curve= 0 ,0
Exp/Cntr=0.3,0.1

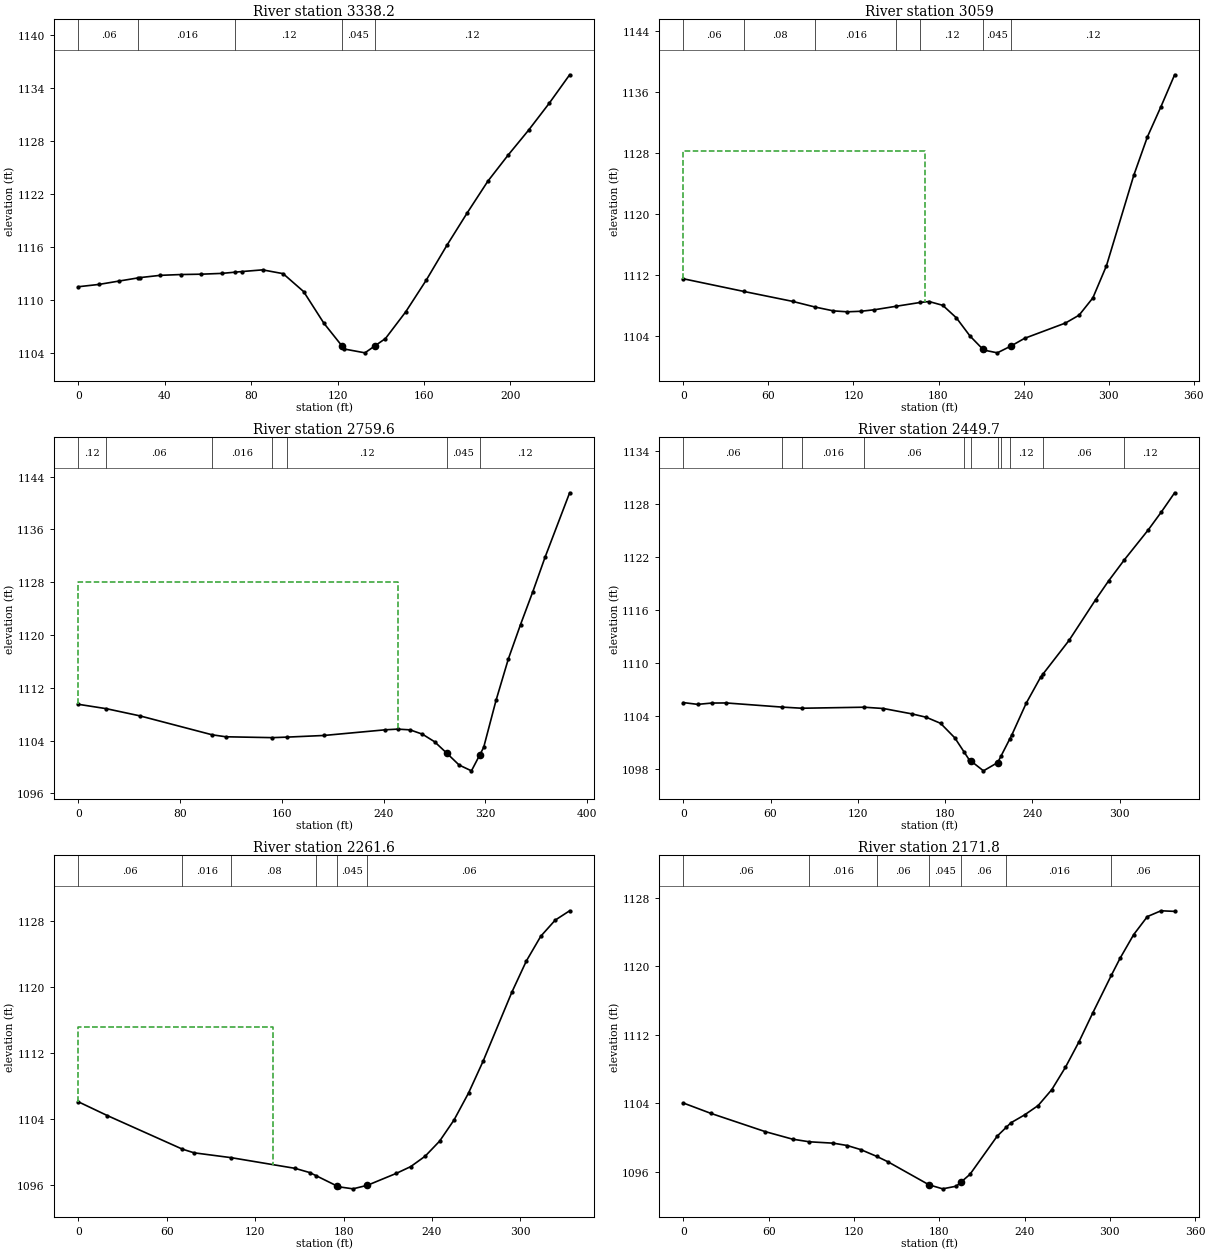
Type RM Length L Ch R = 1 ,3338.2  ,284.1,279.2,274.1
XS GIS Cut Line= 2
     1784112.548      262780.311     1784222.398      262581.116
#Sta/Elev= 29
       0 1111.54     9.5  1111.8      19 1112.19   27.761112.544    28.4 1112.57
    37.9 1112.83    47.4 1112.92    56.9 1112.96    66.4 1113.05   72.471113.186
    75.8 1113.26    85.3 1113.45    94.8 1113.02   104.3 1110.99   113.7  1107.4
   122.2 1104.79   123.2 1104.48   132.7 1104.05   137.2 1104.82   142.2 1105.67
   151.6  1108.7   161.1 1112.29   170.6 1116.21   180.1 1119.92   189.6 1123.49
     199 1126.45   208.5 1129.28     218 1132.31   227.5 1135.55
#Mann= 5 ,-1 , 0
       0     .06       0   27.76    .016       0   72.47     .12       0
   122.2    .045       0   137.2     .12       0
Bank Sta=122.2,137.2
XS Rating Curve= 0 ,0
Exp/Cntr=0.3,0.1

Type RM Length L Ch R = 1 ,3059    ,295.6,299.4,302.7
XS GIS Cut Line= 2
     1784338.889      263005.004     1784463.969       262681.72
#Sta/Elev= 27
       0 1111.54   42.441109.888      77 1108.58   93.03 1107.83   105.9 1107.33
   115.6 1107.21   125.2 1107.28   134.8 1107.48  150.061107.935  167.191108.439
   173.3 1108.56     183 1108.06   192.6 1106.42   202.2 1104.04   211.2 1102.32
   211.8  1102.2   221.5 1101.83   231.1 1102.72   240.7 1103.73   269.6 1105.74
   279.2 1106.77   288.9 1109.03   298.5 1113.25   317.8 1125.12   327.4 1130.15
     337 1134.13   346.6 1138.29
#Mann= 7 ,-1 , 0
       0     .06       0   42.44     .08       0   93.03    .016       0
  150.06     .06       0  167.19     .12       0   211.2    .045       0
   231.1     .12       0
#XS Ineff= 2 , 0
          170.81 1128.27
Permanent Ineff=
       F       F
Bank Sta=211.2,231.1
XS Rating Curve= 0 ,0
Exp/Cntr=0.3,0.1

Type RM Length L Ch R = 1 ,2759.6  ,302.9,309.9,316.6
XS GIS Cut Line= 2
     1784556.593      263164.273     1784731.853      262820.088
#Sta/Elev= 24
       0 1109.51   22.021108.845    48.3 1107.76  105.211104.887   115.9 1104.59
  152.34 1104.46  163.831104.537   193.1 1104.79   241.4 1105.65     251 1105.75
   260.7 1105.64   270.4 1104.99     280 1103.84   289.7 1102.09   299.3 1100.31
     309 1099.43   315.5 1101.83   318.6 1102.98   328.3 1110.09     338 1116.38
   347.6  1121.6   357.3  1126.6   366.9 1131.81   386.2 1141.56
#Mann= 7 ,-1 , 0
       0     .12       0   22.02     .06       0  105.21    .016       0
  152.34     .06       0  163.83     .12       0   289.7    .045       0
   315.5     .12       0
#XS Ineff= 2 , 0
           251.2 1128.11
Permanent Ineff=
       F       F
Bank Sta=289.7,315.5
XS Rating Curve= 0 ,0
Exp/Cntr=0.3,0.1

Type RM Length L Ch R = 1 ,2449.7  ,195.2,188,180.8
XS GIS Cut Line= 3
     1784781.497       263280.08     1784942.493      263069.197
     1784958.129      262998.315
#Sta/Elev= 30
       0 1105.48     9.8 1105.28    19.6 1105.43    29.5 1105.44   67.951104.969
   81.581104.841  124.311104.957   137.6 1104.81   157.2  1104.2     167 1103.82
   176.9 1103.13   186.7 1101.48  193.131099.866   196.5 1099.02     198 1098.83
   206.4 1097.74   216.2 1098.68  218.521099.428  224.511101.359     226 1101.84
   235.8 1105.41   245.7 1108.36  247.131108.671   265.3 1112.54   283.5 1117.14
   292.5 1119.29  303.351121.683   319.8 1125.08   328.8 1127.11   337.9 1129.28
#Mann= 11 ,-1 , 0
       0     .06       0   67.95     .08       0   81.58    .016       0
  124.31     .06       0  193.13     .12       0     198    .045       0
   216.2     .12       0  218.52     .06       0  224.51     .12       0
  247.13     .06       0  303.35     .12       0
Bank Sta=198,216.2
XS Rating Curve= 0 ,0
Exp/Cntr=0.3,0.1

Type RM Length L Ch R = 1 ,2261.6  ,88.9,89.8,90.9
XS GIS Cut Line= 2
     1784995.655      263344.979     1785143.401      263045.968
#Sta/Elev= 24
       0  1106.1    19.6 1104.44   70.521100.378    78.5 1099.93  103.741099.342
   147.1 1098.05     157 1097.54  161.231097.173   175.6 1095.91   176.6 1095.82
   186.4 1095.57   196.2    1096   215.8 1097.44   225.6 1098.26   235.4 1099.52
   245.2 1101.34     255  1103.9   264.9 1107.18   274.7    1111   294.3 1119.38
   304.1 1123.14   313.9 1126.14   323.7 1128.09   333.5 1129.22
#Mann= 6 ,-1 , 0
       0     .06       0   70.52    .016       0  103.74     .08       0
  161.23     .06       0   175.6    .045       0   196.2     .06       0
#XS Ineff= 2 , 0
          131.97 1115.18
Permanent Ineff=
       F       F
Bank Sta=175.6,196.2
XS Rating Curve= 0 ,0
Exp/Cntr=0.3,0.1

Type RM Length L Ch R = 1 ,2171.8  ,171.9,149,126.1
XS GIS Cut Line= 2
     1785082.057      263359.601     1785235.154      263049.762
#Sta/Elev= 30
       0 1104.03    19.2 1102.83    57.6 1100.69    76.8 1099.81   88.581099.504
   105.6 1099.34   115.2 1099.07   124.8 1098.59   136.11097.794     144 1097.16
   172.8 1094.48   182.4 1094.01     192 1094.32   195.4 1094.81   201.6  1095.7
   220.8 1100.17  227.091101.186   230.4 1101.72     240 1102.64   249.6 1103.74
   259.2  1105.6   268.8 1108.21   278.4 1111.21     288 1114.55  301.011118.925
   307.2 1120.93   316.8  1123.7   326.4  1125.8     336 1126.48   345.6 1126.41
#Mann= 7 ,-1 , 0
       0     .06       0   88.58    .016       0   136.1     .06       0
   172.8    .045       0   195.4     .06       0  227.09    .016       0
  301.01     .06       0
Bank Sta=172.8,195.4
XS Rating Curve= 0 ,0
Exp/Cntr=0.3,0.1

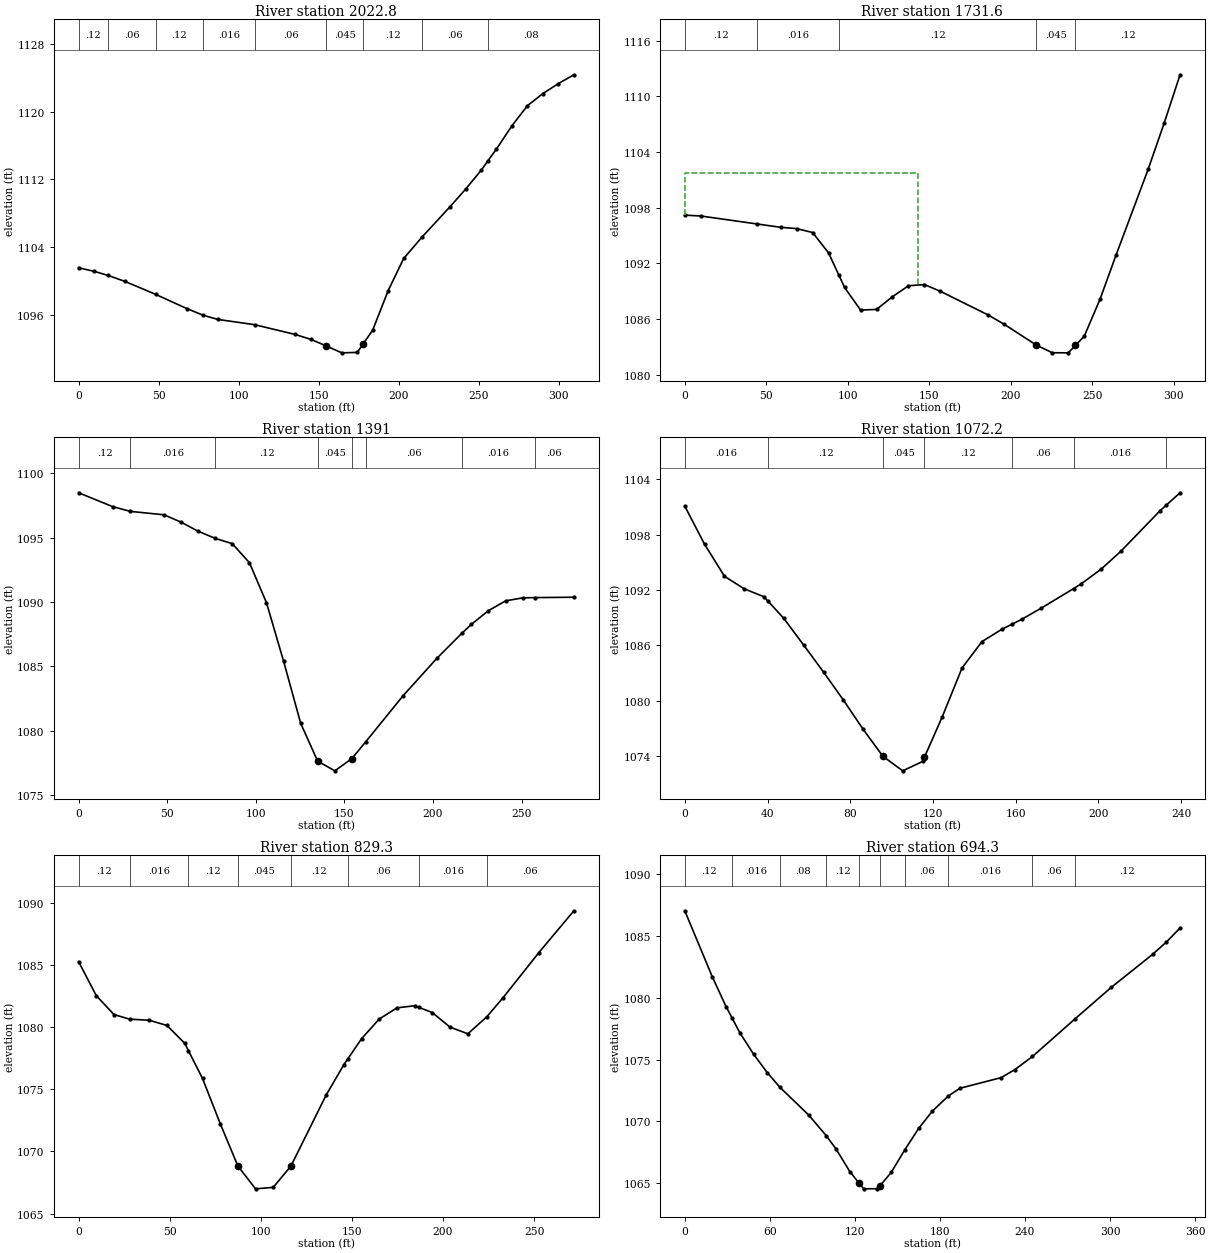
Type RM Length L Ch R = 1 ,2022.8  ,289.8,291.2,292.4
XS GIS Cut Line= 2
     1785334.108      263354.125     1785297.723      263046.672
#Sta/Elev= 29
       0 1101.56     9.7 1101.14   18.491100.651      29 1099.95   48.171098.419
    67.7 1096.74   77.861095.955    87.1 1095.46  109.981094.844   135.4 1093.69
   145.1 1093.11   154.8 1092.34   164.5 1091.52   174.2 1091.57   177.7 1092.53
   183.8 1094.19   193.5 1098.86   203.2 1102.66  214.911105.236   232.2 1108.77
   241.9 1110.84   251.6 1113.06  255.991114.212   261.2 1115.58   270.9 1118.33
   280.6  1120.7   290.2 1122.12   299.9  1123.3   309.6 1124.34
#Mann= 9 ,-1 , 0
       0     .12       0   18.49     .06       0   48.17     .12       0
   77.86    .016       0  109.98     .06       0   154.8    .045       0
   177.7     .12       0  214.91     .06       0  255.99     .08       0
Bank Sta=154.8,177.7
XS Rating Curve= 0 ,0
Exp/Cntr=0.3,0.1

Type RM Length L Ch R = 1 ,1731.6  ,308.3,340.6,372.6
XS GIS Cut Line= 2
     1785582.919      263316.762     1785561.896      263013.673
#Sta/Elev= 27
       0 1097.21     9.8 1097.12    44.3 1096.26    58.8  1095.9    68.6 1095.76
    78.4 1095.34    88.2 1093.14   94.451090.768      98 1089.42   107.8 1086.98
   117.6 1087.05   127.4 1088.42   137.2  1089.6     147 1089.73   156.8    1089
   186.2 1086.44     196 1085.44   215.6 1083.21   225.4 1082.38   235.2 1082.37
   239.6 1083.17     245 1084.15   254.8 1088.19   264.6 1092.94   284.2 1102.14
     294  1107.1   303.8 1112.34
#Mann= 5 ,-1 , 0
       0     .12       0    44.3    .016       0   94.45     .12       0
   215.6    .045       0   239.6     .12       0
#XS Ineff= 2 , 0
             143  1101.7
Permanent Ineff=
       F       F
Bank Sta=215.6,239.6
XS Rating Curve= 0 ,0
Exp/Cntr=0.3,0.1

Type RM Length L Ch R = 1 ,1391    ,341.4,318.7,296
XS GIS Cut Line= 2
     1785735.205       263366.44     1785931.362      263167.334
#Sta/Elev= 25
       0 1098.48    19.3  1097.4   29.211097.035    48.2 1096.77    57.8  1096.2
    67.5 1095.49   77.171094.937    86.7 1094.53    96.4 1093.05     106 1089.95
   115.7 1085.39   125.3 1080.59   134.9 1077.64   144.6 1076.89   154.2 1077.84
  162.041079.147   183.1 1082.72   202.4 1085.66  216.251087.568   221.7 1088.27
   231.3 1089.33     241 1090.09   250.6 1090.32  257.441090.341   279.5 1090.37
#Mann= 8 ,-1 , 0
       0     .12       0   29.21    .016       0   77.17     .12       0
   134.9    .045       0   154.2     .12       0  162.04     .06       0
  216.25    .016       0  257.44     .06       0
Bank Sta=134.9,154.2
XS Rating Curve= 0 ,0
Exp/Cntr=0.3,0.1

Type RM Length L Ch R = 1 ,1072.2  ,248.6,242.9,237.2
XS GIS Cut Line= 2
     1786070.013      263537.716     1786111.689      263301.873
#Sta/Elev= 29
       0  1101.1     9.6 1096.95    19.2 1093.49    28.7 1092.14    38.3 1091.27
   40.26 1090.79    47.9 1088.92    57.5 1086.03    67.1  1083.1    76.6  1080.1
    86.2 1076.91    95.8 1073.97   105.4 1072.39     115 1073.41   115.9 1073.87
   124.5 1078.25   134.1 1083.56   143.7 1086.41   153.3 1087.74     1581088.269
   162.9 1088.82   172.4 1090.04  188.091092.167   191.6 1092.66   201.2 1094.24
   210.8 1096.19   229.9 1100.62  232.721101.187   239.5 1102.55
#Mann= 7 ,-1 , 0
       0    .016       0   40.26     .12       0    95.8    .045       0
   115.9     .12       0     158     .06       0  188.09    .016       0
  232.72     .06       0
Bank Sta=95.8,115.9
XS Rating Curve= 0 ,0
Exp/Cntr=0.3,0.1

Type RM Length L Ch R = 1 ,829.3   ,140.5,135,129.5
XS GIS Cut Line= 2
     1786326.029      263565.002      1786332.89      263293.289
#Sta/Elev= 29
       0 1085.29     9.7 1082.55    19.4 1081.03   27.95 1080.66    38.8 1080.57
    48.5 1080.15    58.2 1078.72   60.27 1078.12      68 1075.88    77.7 1072.25
    87.4 1068.83    97.1 1066.99   106.8 1067.11   116.5 1068.82   135.9 1074.56
   145.6    1077  147.561077.422   155.3 1079.09     165 1080.67   174.7 1081.57
   184.4 1081.74  186.811081.603   194.1 1081.19   203.8 1080.02   213.6 1079.48
   223.91080.833     233  1082.4   252.4 1085.99   271.8 1089.39
#Mann= 8 ,-1 , 0
       0     .12       0   27.95    .016       0   60.27     .12       0
    87.4    .045       0   116.5     .12       0  147.56     .06       0
  186.81    .016       0   223.9     .06       0
Bank Sta=87.4,116.5
XS Rating Curve= 0 ,0
Exp/Cntr=0.3,0.1

Type RM Length L Ch R = 1 ,694.3   ,96.8,97,97.3
XS GIS Cut Line= 2
     1786471.191      263560.999     1786431.385      263213.889
#Sta/Elev= 30
       0 1087.01    19.4 1081.68    29.1 1079.28   33.461078.332    38.8 1077.17
    48.5 1075.44    58.2 1073.94   67.231072.748    87.4 1070.52   99.791068.854
   106.8 1067.76   116.5 1065.94   122.7 1065.06   126.2 1064.56   135.9 1064.57
   137.7 1064.81   145.6 1065.88  155.031067.678     165 1069.44   174.7 1070.84
  185.941072.057   194.1 1072.68   223.2 1073.54   232.9 1074.19  245.291075.247
  274.97 1078.25   300.9 1080.83     330 1083.49   339.7 1084.48   349.4 1085.62
#Mann= 10 ,-1 , 0
       0     .12       0   33.46    .016       0   67.23     .08       0
   99.79     .12       0   122.7    .045       0   137.7     .12       0
  155.03     .06       0  185.94    .016       0  245.29     .06       0
  274.97     .12       0
Bank Sta=122.7,137.7
XS Rating Curve= 0 ,0
Exp/Cntr=0.3,0.1

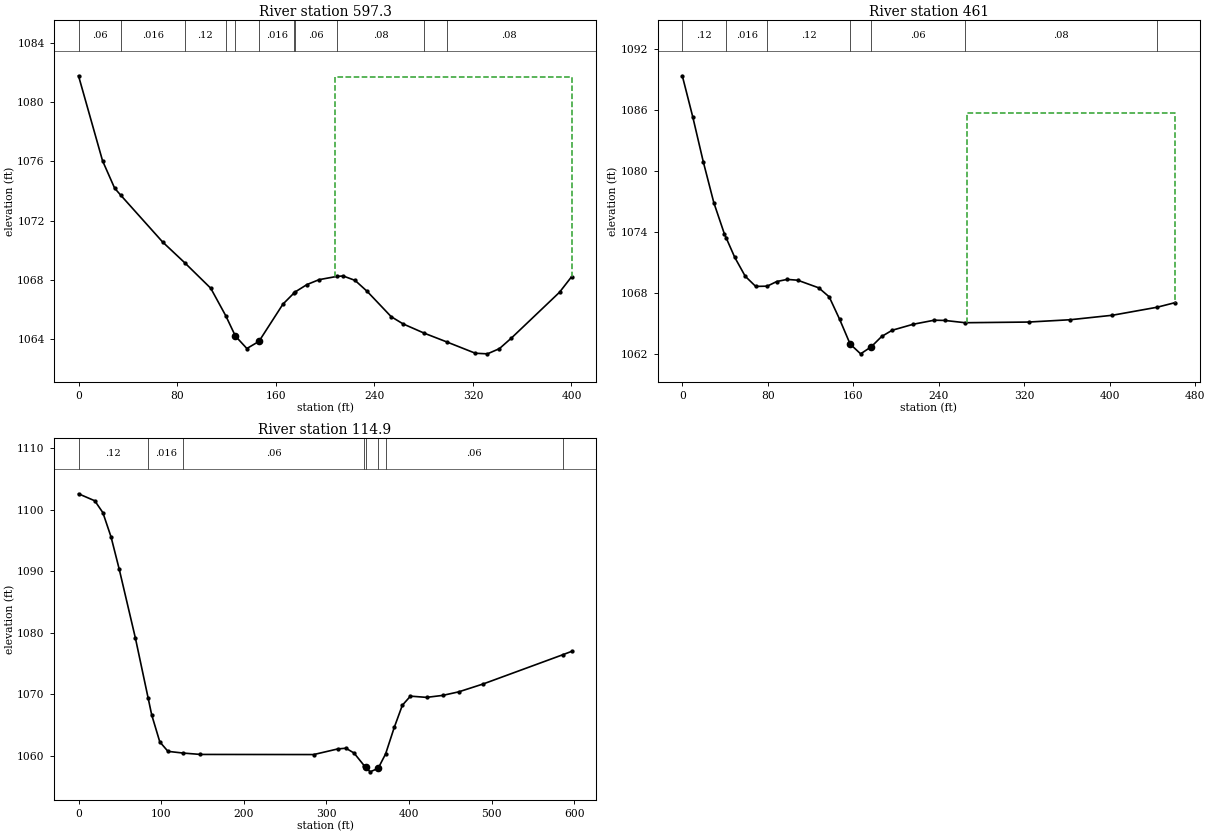
Type RM Length L Ch R = 1 ,597.3   ,137.1,136.2,134.7
XS GIS Cut Line= 2
     1786566.279      263549.588     1786523.254      263151.848
#Sta/Elev= 30
       0 1081.78    19.5 1076.04    29.3 1074.19   34.281073.713    68.3 1070.55
   86.191069.151   107.3 1067.43  119.43 1065.58   127.3  1064.2   136.6 1063.36
   146.4 1063.84   165.9 1066.36  175.061067.125  175.861067.184   185.4 1067.68
   195.2 1068.01  209.541068.228   214.7 1068.26   224.4 1067.96   234.2 1067.22
   253.7 1065.51   263.4 1065.02  280.721064.389  298.831063.804     322 1063.04
   331.8    1063   341.5 1063.35   351.3 1064.07   390.3 1067.16   400.1 1068.21
#Mann= 11 ,-1 , 0
       0     .06       0   34.28    .016       0   86.19     .12       0
  119.43    .016       0   127.3    .045       0   146.4    .016       0
  175.06     .12       0  175.86     .06       0  209.54     .08       0
  280.72     .06       0  298.83     .08       0
#XS Ineff= 2 , 0
                          208.07         1081.72
Permanent Ineff=
       F       F
Bank Sta=127.3,146.4
XS Rating Curve= 0 ,0
Exp/Cntr=0.3,0.1

Type RM Length L Ch R = 1 ,461     ,326.9,346.2,365.5
XS GIS Cut Line= 2
     1786707.575      263568.805     1786641.908      263111.965
#Sta/Elev= 30
       0 1089.35     9.8  1085.3    19.6  1080.9    29.5 1076.86    39.3 1073.81
   40.931073.421    49.1 1071.47    58.9 1069.61    68.7 1068.61   79.441068.633
    88.4 1069.09    98.2  1069.3     108 1069.22   127.7 1068.47   137.5 1067.58
   147.3 1065.36   157.1 1062.93   166.9 1061.97   176.8 1062.66   186.6 1063.68
   196.4 1064.29     216 1064.88   235.7 1065.28   245.5 1065.26  264.761065.034
   324.1  1065.1   363.3 1065.33   402.6 1065.77  444.44 1066.56   461.5 1067.02
#Mann= 7 ,-1 , 0
       0     .12       0   40.93    .016       0   79.44     .12       0
   157.1    .045       0   176.8     .06       0  264.76     .08       0
  444.44     .06       0
#XS Ineff= 2 , 0
                          266.08         1085.71
Permanent Ineff=
       F       F
Bank Sta=157.1,176.8
XS Rating Curve= 0 ,0
Exp/Cntr=0.3,0.1

Type RM Length L Ch R = 1 ,114.9   ,113.9,114.9,116
XS GIS Cut Line= 3
     1786859.865       263696.75     1786973.454      263524.094
     1787114.863      263160.431
#Sta/Elev= 30
       0  1102.6    19.7 1101.46    29.5 1099.53    39.4 1095.58    49.2 1090.38
    68.9 1079.11   84.371069.328    88.6 1066.64    98.4 1062.25   108.3 1060.71
  126.561060.434   147.6 1060.21   284.7 1060.19     314 1061.11   323.7 1061.22
   333.5 1060.44  346.011058.353   347.7 1058.12     353 1057.38   362.7 1057.95
  371.73 1060.29   382.2  1064.6     392 1068.21   401.8 1069.69   421.3 1069.49
   440.8 1069.81   460.3 1070.39   489.6 1071.66  586.041076.415   596.9 1076.97
#Mann= 8 ,-1 , 0
       0     .12       0   84.37    .016       0  126.56     .06       0
  346.01     .12       0   347.7    .045       0   362.7     .12       0
  371.73     .06       0  586.04     .12       0
Bank Sta=347.7,362.7
XS Rating Curve= 0 ,0
Exp/Cntr=0.3,0.1

Chan Stop Cuts=-1
Use User Specified Reach Order=0
Composite Channel Slope=5